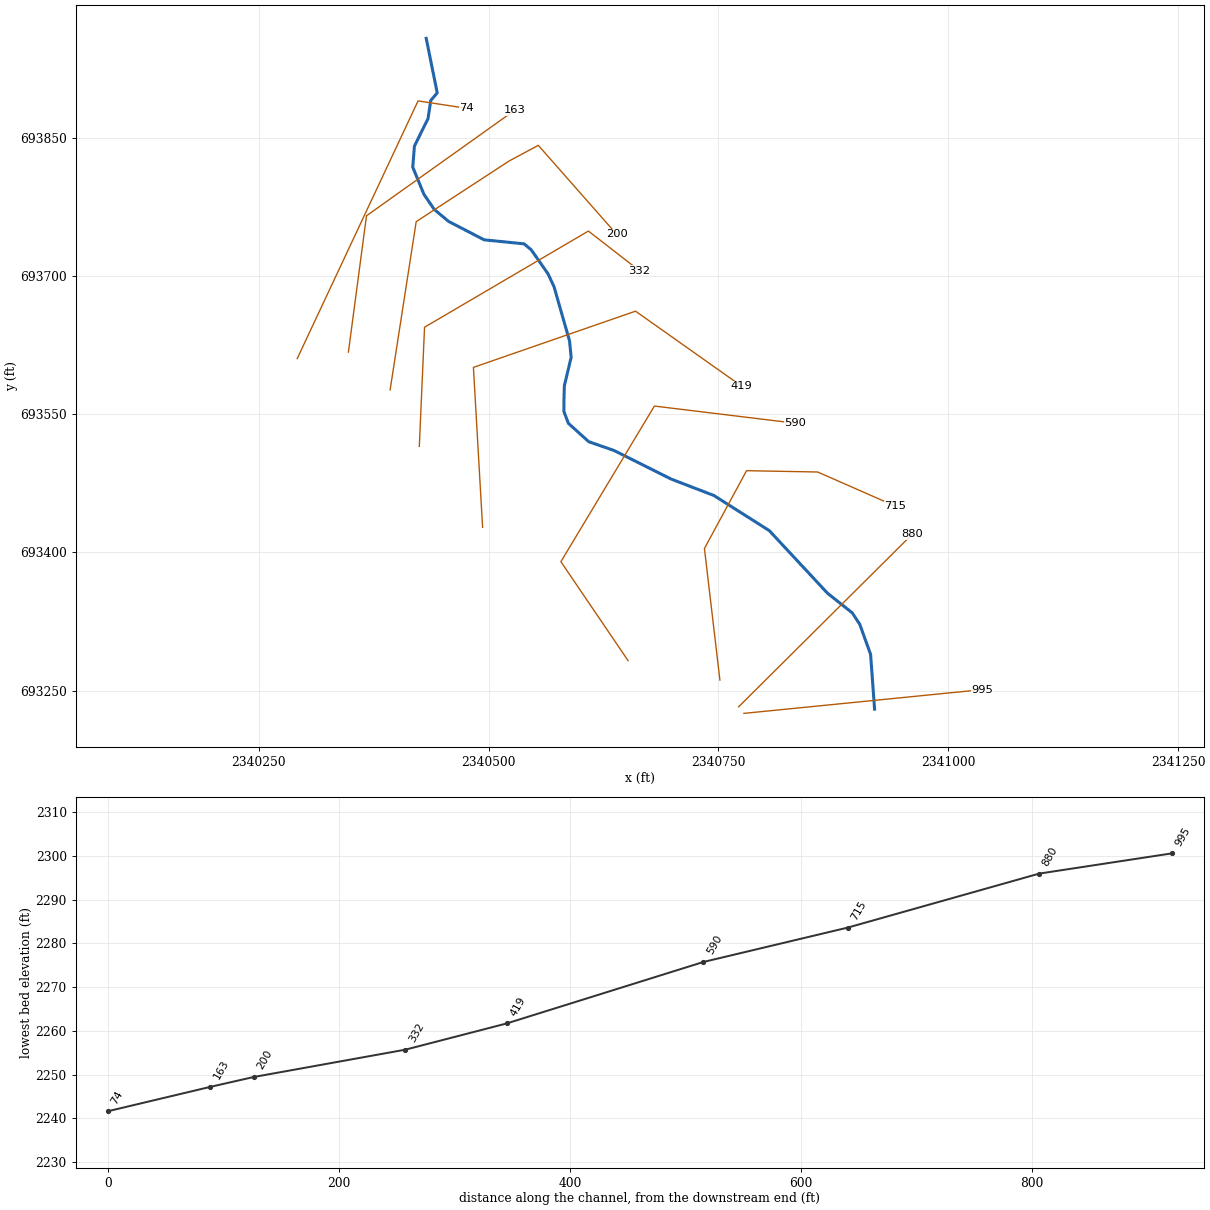
--- WLSONRN.prj (project) ---

Proj Title=WLSONRN
Current Plan=p01
Default Exp/Contr=0,0
English Units
Geom File=g01
Flow File=f01
Plan File=p01
BEGIN DESCRIPTION:
----------MODEL BY WOOD PLC 2022----------
AFH study
Randolph County, WV
HEC-RAS Version: RAS 6.2
Vertical Datum: NAVD88
Projection: NAD 1983 StatePlane West Virginia S FIPS 4702 (US Feet)
Terrain: 1-meter LIDAR (FEMA Region III 3DEP collected 2016-2018)
Land Use: 2019 NLCD
Hydrologic Method:
WV SIR2010-5033 regression equations
Additional Model Notes:
None
END DESCRIPTION:
DSS Export Rating Curves= 0
DSS Export Rating Curve Sorted= 0
DSS Export Volume Flow Curves= 0
DXF OffsetX= 0
DXF OffsetY= 0
DXF ScaleX= 0
DXF ScaleY= 0

--- WLSONRN.p01 (plan) ---

Plan Title=Floodplain
Program Version=6.20
Short Identifier=Floodplain
Geom File=g01
Flow File=f01
Subcritical Flow
K Sum by GR= 0
Std Step Tol= 0.01
Critical Tol= 0.01
Num of Std Step Trials= 20
Max Error Tol= 0.3
Flow Tol Ratio= 0.001
Split Flow NTrial= 30
Split Flow Tol= 0.02
Split Flow Ratio= 0.02
Log Output Level= 0
Friction Slope Method= 1
Unsteady Friction Slope Method= 2
Unsteady Bridges Friction Slope Method= 1
Parabolic Critical Depth
Global Vel Dist= 0 , 0 , 0
Global Log Level= 0
CheckData=True
Encroach Param=-1 ,0,0, 0
Mapping Interval=1HOUR
Computation Time Step Use Courant=        0
Computation Time Step Use Time Series=    0
Computation Time Step Count To Double=0
Computation Time Step Max Doubling=0
Computation Time Step Max Halving=0
Computation Time Step Residence Courant=0
Run HTab= 0
Run UNet= 0
Run Sediment= 0
Run PostProcess= 0
Run WQNet= 0
Run RASMapper=-1
UNET Theta= 0
UNET Theta Warmup= 0
UNET ZTol= 0
UNET ZSATol= 0
UNET MxIter= 0
UNET Max Iter WO Improvement= 0
UNET MaxInSteps= 0
UNET DtIC= 0
UNET DtMin= 0
UNET MaxCRTS= 0
UNET WFStab= 0
UNET SFStab= 0
UNET WFX= 1
UNET SFX= 1
UNET Gravity=32.174
UNET 1D Methodology=Finite Difference
UNET DSS MLevel= 1
UNET Pardiso=0
UNET DZMax Abort= 0
UNET Use Existing IB Tables= 0
UNET Froude Reduction=False
UNET Froude Limit= 0
UNET Froude Power= 0
UNET D1 Cores= 0
UNET WindReference=Eulerian
UNET WindDragFormulation=Hsu (1988)
UNET D2 Coriolis=0
UNET D2 Cores= 0
UNET D2 Theta= 1
UNET D2 Theta Warmup= 1
UNET D2 Z Tol= 0.01
UNET D2 Volume Tol= 0.01
UNET D2 Max Iterations= 20
UNET D2 Equation= 0
UNET D2 RampUpFraction=0.1
UNET D2 TimeSlices= 1
UNET D2 Turbulence Formulation=Non-Conservative (original)
UNET D2 Eddy Viscosity=0.3
UNET D2 Transverse Eddy Viscosity=0.1
UNET D2 Smagorinsky Mixing=0
UNET D2 BCVolumeCheck=0
UNET D2 Cores=0
UNET D2 SolverType=PARDISO (Direct)
UNET D2 Minimum Iterations= 2147483647
UNET D2 Maximum Iterations= 2147483647
UNET D2 Restart Number= 10
UNET D2 Relaxation Coeff=1.3
UNET D2 SOR Precondition Iterations= 10
UNET D2 ILUT Maximum Fill= 8
UNET D2 ILUT Tolerance=1E-08
UNET D1D2 MaxIter= 0
UNET D1D2 ZTol=0.01
UNET D1D2 QTol=0.1
UNET D1D2 MinQTol=1
Write IC File= 0
Write IC File at Fixed DateTime=0
Write IC File at Sim End=0
Echo Input=False
Echo Parameters=False
Echo Output=False
Write Detailed= 0
HDF Write Warmup=0
HDF Write Time Slices=0
HDF Flush=0
HDF Compression= 1
HDF Chunk Size= 1
HDF Spatial Parts= 1
HDF Use Max Rows=0
HDF Fixed Rows= 1
Calibration Method= 0
Calibration Iterations= 20
Calibration Max Change=0.05
Calibration Tolerance=0.2
Calibration Maximum=1.5
Calibration Minimum=0.5
Calibration Optimization Method= 1
WQ AD Non Conservative
WQ ULTIMATE=-1
WQ Max Comp Step=1HOUR
WQ Output Interval=15MIN
WQ Output Selected Increments= 0
WQ Output face flow=0
WQ Output face velocity=0
WQ Output face area=0
WQ Output face dispersion=0
WQ Output cell volume=0
WQ Output cell surface area=0
WQ Output cell continuity=0
WQ Output cumulative cell continuity=0
WQ Output face conc=0
WQ Output face dconc_dx=0
WQ Output face courant=0
WQ Output face peclet=0
WQ Output face adv mass=0
WQ Output face disp mass=0
WQ Output cell mass=0
WQ Output cell source sink temp=0
WQ Output nsm pathways=0
WQ Output nsm derived pathways=0
WQ Create Restart=0
WQ Fixed Restart=0
WQ System Summary=0
WQ Write To DSS=0
Sorting and Armoring Iterations= 10
XS Update Threshold= 0.02
Bed Roughness Predictor= 0
Hydraulics Update Threshold= 0.02
Energy Slope Method= 1
Volume Change Method= 1
Sediment Retention Method= 0
Sediment TS Multiplier= 1
Warm Up Method= 0
XS Weighting Method= 0
Number of US Weighted Cross Sections= 1
Number of DS Weighted Cross Sections= 1
Upstream XS Weight=0
Main XS Weight=1
Downstream XS Weight=0
Number of DS XS's Weighted with US Boundary= 1
Upstream Boundary Weight= 1
Weight of XSs Associated with US Boundary= 0
Number of US XS's Weighted with DS Boundary= 1
Downstream Boundary Weight= 0.5
Weight of XSs Associated with DS Boundary= 0.5
Percentile Method= 0
Sediment Output Level= 3
Mass or Volume Output= 0
Output Increment Type= 1
Profile and TS Output Increment= 1
Transport Output Increment 1
XS Output Flag= 0
XS Output Increment= 10
Read HDF5 Sediment Hotstart= 0
Sediment Hotstart Type= 0
Write Gradation File= 0
Read Gradation Hotstart= 0
Write HDF5 File= 1
Write Binary Output= 1
Write DSS Sediment File= 0
DSS Sediment Output Type= 1
SV Curve= 0
Specific Gage Flag= 0
Subcell Erosion Methods= 0
Subcell Deposition Methods= 0
Advection Scheme= 1
Matrix Solver= 0
Implicit Weighting Factor= 1
Maximum Outer Loop Convergence Iterations= 5
Convergence Maximum Absolute= 0.001
Convergence RMSE= 0.0001
Grain Fractions Max Abs Error= 0.001
Max Subgrid Regions= 1
Max Subgrid Length Scale= 3.402823E+38
Initial Layer Thickness= 3.402823E+38
Min Layer Thickness= 3.402823E+38
Max Layer Thickness= 3.402823E+38
Number of Layers= 5

--- WLSONRN.f01 (steady flow) ---

Flow Title=Flow
Program Version=6.20
Number of Profiles= 1
Profile Names=P100yr
River Rch & RM=WLSONRN,Main,995
     303
Boundary for River Rch & Prof#=WLSONRN,Main            , 1
Up Type= 0
Dn Type= 3
Dn Slope=0.10813
DSS Import GetInterval= 0
DSS Import GetPeak= 0
DSS Import FillOption= 0

--- WLSONRN.g01 (geometry) ---

Geom Title=Geometry
Program Version=6.20

River Reach=WLSONRN         ,Main
Reach XY= 30
     2340919.811      693229.826      2340915.47      693289.287
     2340903.752      693321.839     2340895.505      693334.426
     2340868.595      693355.694     2340805.314      693423.662
     2340744.984      693461.857     2340698.543      693479.652
      2340636.64      693510.595     2340608.862       693520.27
     2340586.727      693540.235     2340581.952      693552.822
     2340581.952      693566.277     2340582.386      693581.034
     2340589.765       693611.85     2340588.029      693629.645
     2340571.102      693688.672     2340564.591      693702.561
     2340546.362      693728.603     2340538.549      693735.114
     2340495.147      693739.454     2340456.518      693759.419
     2340440.894       693772.44     2340429.609      693788.933
     2340417.456      693818.447 2340419.3123195693841.269741899
2340434.06488947693871.0623670332340437.07915643 693890.81250447
2340444.08834191693899.009443831     2340432.112      693958.273

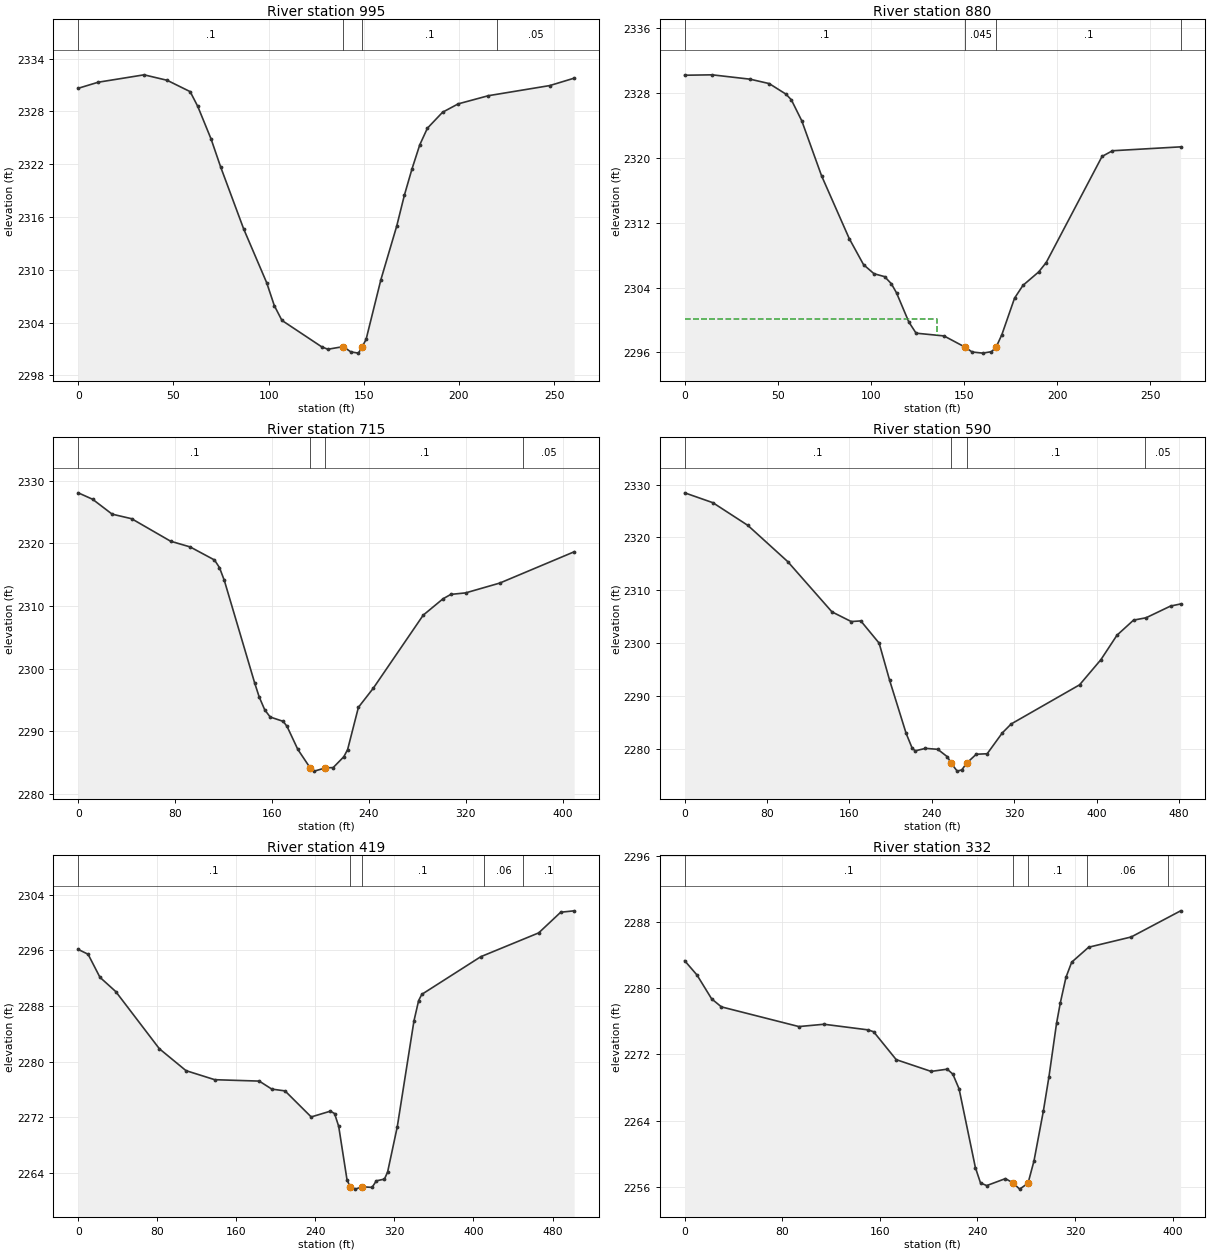
Type RM Length L Ch R = 1 ,995     ,110.2,114.6,120.1
XS GIS Cut Line= 2
2340777.70175582693225.2251232392341036.94624874693251.006343529
#Sta/Elev= 30
       0 2330.63    10.5 2331.32    34.6 2332.16    46.7 2331.54    58.8 2330.25
    62.8 2328.57    69.8 2324.86    74.8  2321.7    86.9 2314.65      99 2308.53
     103 2305.93     107 2304.25   127.8 2301.26   131.1 2300.97   139.2 2301.27
   143.2 2300.67   147.2 2300.53   149.22301.279   151.2 2302.08     159 2308.89
   167.3 2314.97   171.3 2318.46   175.3 2321.45   179.4  2324.2   183.4 2326.09
   191.4 2327.91   199.6 2328.86   215.5 2329.79   247.7 2330.94   260.5 2331.78
#Mann= 4 ,-1,0
       0      .1       0   139.2    .045       0   149.2      .1       0
     220     .05       0
Bank Sta=139.2,149.2
XS Rating Curve= 0 ,0
Exp/Cntr(USF)=0,0
Exp/Cntr=0.3,0.1

Type RM Length L Ch R = 1 ,880     ,163.3,165.7,167.2
XS GIS Cut Line= 2
2340771.97259575 693232.386573322340961.03487788693420.016565431
#Sta/Elev= 30
       0 2330.18    14.8 2330.23    35.2 2329.69    45.4 2329.15    54.4 2327.85
    57.3 2327.15    62.9 2324.56    73.5  2317.8    88.4 2310.04    96.1 2306.82
   101.7 2305.71   107.4 2305.35     111 2304.48   113.8 2303.35   120.4 2299.76
   124.3 2298.38   139.3 2298.04   150.6 2296.66   154.4 2296.06   160.1 2295.92
   164.8  2296.1  167.282296.648   170.4 2298.21   177.2  2302.7   181.7 2304.27
   190.2 2305.94   194.2 2307.09   224.2 2320.17   229.8 2320.87   266.4 2321.35
#Mann= 4 ,-1,0
       0      .1       0   150.6    .045       0  167.28      .1       0
  266.36     .05       0
#XS Ineff= 2 , 0
          135.47 2300.12
Permanent Ineff=
       F       F
Bank Sta=150.6,167.28
XS Rating Curve= 0 ,0
Exp/Cntr(USF)=0,0
Exp/Cntr=0.3,0.1

Type RM Length L Ch R = 1 ,715     ,125,124.9,124.2
XS GIS Cut Line= 5
2340751.57523462 693261.410082452340734.73305534693404.261375254
2340780.56633585693488.7664862042340857.90999672693487.334196188
2340942.24531368693450.342567309
#Sta/Elev= 30
       0 2328.09    11.9 2327.06      28 2324.68    44.1 2323.95    76.3 2320.35
    92.4 2319.44   112.5 2317.35   116.6 2316.14   120.6 2314.09   145.6 2297.73
   149.4 2295.45     154 2293.38   158.5 2292.24   169.2 2291.55   172.4 2290.74
   181.3 2287.06   191.62284.075   194.9 2283.59     204  2284.1   210.5 2284.16
   219.3  2285.9   222.4 2287.04   231.3 2293.79   243.6 2296.85   284.8 2308.53
   301.1 2311.14   307.6 2311.85   319.8 2312.09     348 2313.66   409.4 2318.66
#Mann= 4 ,-1,0
       0      .1       0   191.6    .045       0     204      .1       0
  367.33     .05       0
Bank Sta=191.6,204
XS Rating Curve= 0 ,0
Exp/Cntr=0.3,0.1

Type RM Length L Ch R = 1 ,590     ,174,170.4,163.8
XS GIS Cut Line= 4
 2340651.6602344693282.5167238842340578.61344358693389.938475093
2340680.30603472693558.9486969942340833.56106645693540.328926784
#Sta/Elev= 30
       0 2328.43    27.4 2326.56    61.3 2322.27     100 2315.42     143 2305.89
   161.7 2304.06     171 2304.18   188.8 2299.97     199 2292.92     215 2282.89
   220.8 2280.12   223.8 2279.58   233.8 2280.05   245.7 2279.87   255.1 2278.45
   258.7 2277.24   264.6 2275.74   269.1 2275.98   273.7 2277.24   283.1 2278.94
   293.7 2279.03   308.3 2282.96     317 2284.67   383.4 2292.08   404.1 2296.84
   419.7 2301.47   435.8 2304.33   447.9 2304.77   471.7 2306.99   481.5 2307.39
#Mann= 4 ,-1,0
       0      .1       0   258.7    .045       0   273.7      .1       0
  447.15     .05       0
Bank Sta=258.7,273.7
XS Rating Curve= 0 ,0
Exp/Cntr(USF)=0,0
Exp/Cntr=0.3,0.1

Type RM Length L Ch R = 1 ,419     ,86.5,87.6,89
XS GIS Cut Line= 4
2340493.43938211693427.2409415042340483.46647596693600.941562136
2340659.79751982693661.9889911982340775.26216746693580.486171195
#Sta/Elev= 30
       0 2296.13      10 2295.43      22 2292.12      38 2290.07    82.1 2281.86
   109.1 2278.71   138.2 2277.41   183.2 2277.21   195.9 2276.06   209.3  2275.8
   235.8 2272.06   255.2 2272.89   259.4 2272.55   263.6 2270.72   272.1 2262.97
   275.3 2262.05   280.6 2261.69  287.022262.027   297.4 2261.94   301.7 2262.88
   309.9 2263.13   313.1 2264.14   322.9 2270.65   339.8 2285.87   344.5 2288.77
   347.7 2289.67   407.4 2295.08     466  2298.5   488.3 2301.47   501.9 2301.67
#Mann= 5 ,-1,0
       0      .1       0   275.3    .045       0  287.02      .1       0
  410.59     .06       0  450.59      .1       0
Bank Sta=275.3,287.02
XS Rating Curve= 0 ,0
Exp/Cntr(USF)=0,0
Exp/Cntr=0.3,0.1

Type RM Length L Ch R = 1 ,332     ,129,131.4,130.2
XS GIS Cut Line= 4
 2340424.6219391693515.135847852 2340430.2979752693644.549471039
2340608.52550889693748.9885353652340664.15066272693705.850660969
#Sta/Elev= 30
       0 2283.32    10.1 2281.59    22.1 2278.71    30.1 2277.74    93.6 2275.36
   114.2 2275.64   150.3 2274.96   154.9 2274.73   173.4 2271.36     202 2269.94
   215.2 2270.21   219.8 2269.61   224.9 2267.84   238.3  2258.3   242.5 2256.45
   247.6 2256.14   262.9 2256.98   268.8 2256.49   274.6 2255.71  281.432256.426
   286.3 2259.11     294 2265.15   298.6 2269.31   304.8 2275.75   307.9 2278.23
   312.5  2281.3   317.2 2283.14   331.1 2284.95     366 2286.19   406.5 2289.35
#Mann= 5 ,-1,0
       0      .1       0   268.8    .045       0  281.43      .1       0
  329.54     .06       0  396.11      .1       0
Bank Sta=268.8,281.43
XS Rating Curve= 0 ,0
Exp/Cntr(USF)=0,0
Exp/Cntr=0.3,0.1

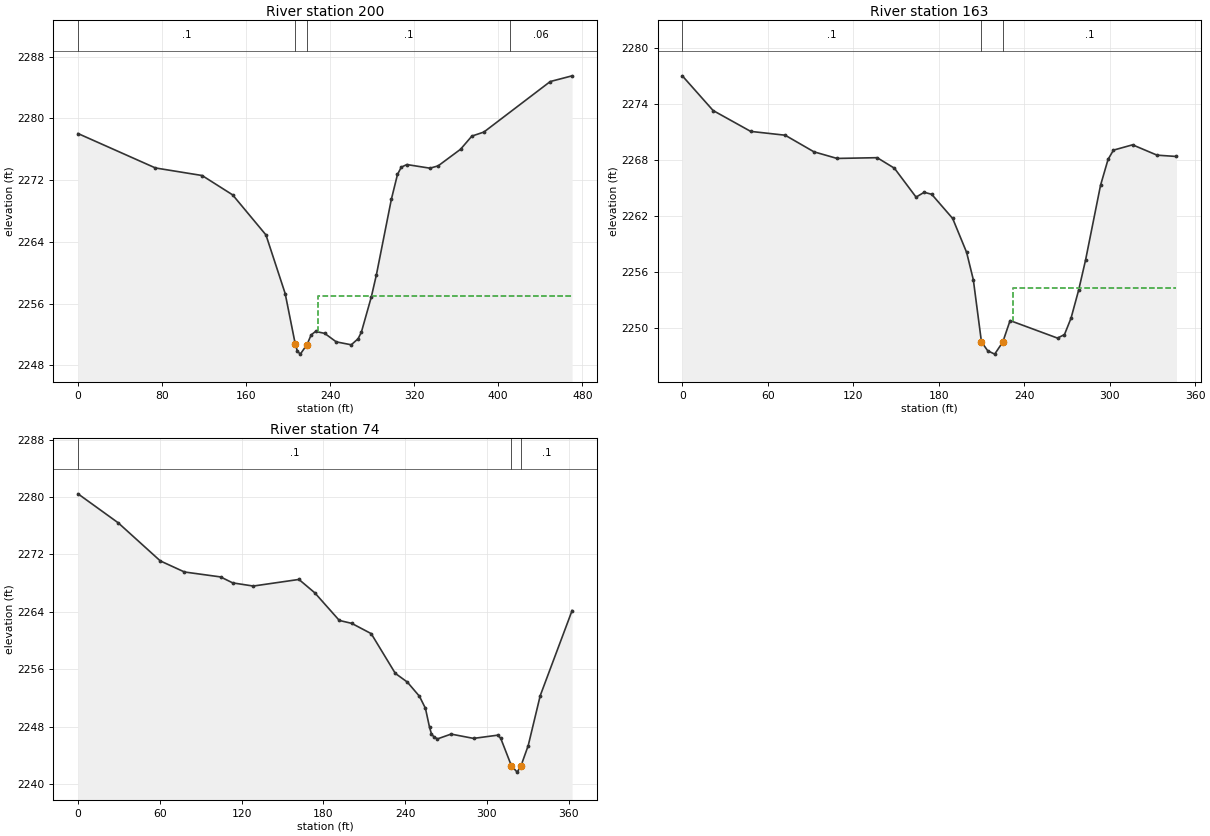
Type RM Length L Ch R = 1 ,200     ,37.6,37.8,38
XS GIS Cut Line= 5
2340392.83613691693576.4370377822340421.21631744693759.205400353
 2340522.2497601693825.0474191672340554.03556229693842.075527482
2340639.17610386693745.582913702
#Sta/Elev= 30
       0 2278.05    73.7 2273.59   118.1 2272.61   147.2  2270.1   178.9 2264.91
   197.2 2257.31  206.72 2250.82   208.8 2249.84   211.6 2249.46  218.012250.705
   221.9 2251.95   226.1  2252.4   234.8 2252.15   245.8 2251.05   260.1 2250.67
   266.6 2251.45   269.7  2252.3   279.2 2256.88     284 2259.73   298.3 2269.55
   304.1 2272.75   307.7 2273.69     313 2274.03     335 2273.56   342.8 2273.86
   364.1 2276.01   374.9 2277.72   386.3 2278.24   449.5 2284.79   470.3 2285.53
#Mann= 4 ,-1,0
       0      .1       0  206.72    .045       0  218.01      .1       0
  411.61     .06       0
#XS Ineff= 2 , 0
                          228.16         2256.95
Permanent Ineff=
       F       F
Bank Sta=206.72,218.01
XS Rating Curve= 0 ,0
Exp/Cntr(USF)=0,0
Exp/Cntr=0.3,0.1

Type RM Length L Ch R = 1 ,163     ,93.6,88.3,81.8
XS GIS Cut Line= 3
2340347.48416171 693617.560908392340367.15390186693765.558468102
2340528.18621022693880.035421471
#Sta/Elev= 30
       0 2277.04    21.6 2273.32      48 2271.08    72.2 2270.67    92.4 2268.89
   108.6 2268.18   136.8 2268.26   148.9 2267.13   164.1 2264.03   169.8 2264.55
   175.1 2264.33   189.8 2261.74   199.6  2258.1   204.3 2255.17     210 2248.51
   214.4 2247.55   219.3 2247.19     2252248.493   230.1 2250.79   263.4 2248.91
   268.3 2249.29   272.9 2251.05   278.2 2254.03   283.1 2257.28   293.6 2265.29
   298.9 2268.08   302.7 2269.07   316.1 2269.64   333.3 2268.53   346.9 2268.39
#Mann= 3 ,-1,0
       0      .1       0     210    .045       0     225      .1       0
#XS Ineff= 2 , 0
                          232.13         2254.24
Permanent Ineff=
       F       F
Bank Sta=210,225
XS Rating Curve= 0 ,0
Exp/Cntr=0.3,0.1

Type RM Length L Ch R = 1 ,74      ,,,
XS GIS Cut Line= 3
2340291.80269425 693610.493254412340423.24517415693890.306995584
2340475.97580531693882.339174613
#Sta/Elev= 30
       0 2280.43    29.5 2276.39    60.4 2271.08    78.1 2269.54   104.6 2268.85
   113.5 2268.02   128.6 2267.58   162.1  2268.5   173.7 2266.64   191.7 2262.79
   200.8 2262.38   215.1 2260.95   232.8 2255.41   241.6  2254.2   250.5 2252.22
   254.9 2250.54   257.9  2247.9   259.3 2246.99   260.9 2246.61   263.7 2246.28
   273.7 2246.95   290.2 2246.35   307.9  2246.8   310.1 2246.38     318 2242.52
   322.2 2241.65     325 2242.53   330.3 2245.35   339.1  2252.3   362.5 2264.17
#Mann= 3 ,0,0
       0      .1       0     318    .045       0     325      .1       0
Bank Sta=318,325
XS Rating Curve= 0 ,0
Exp/Cntr(USF)=0,0
Exp/Cntr=0.3,0.1
LCMann Table=0

Chan Stop Cuts=-1
Use User Specified Reach Order=0
Composite Channel Slope=5